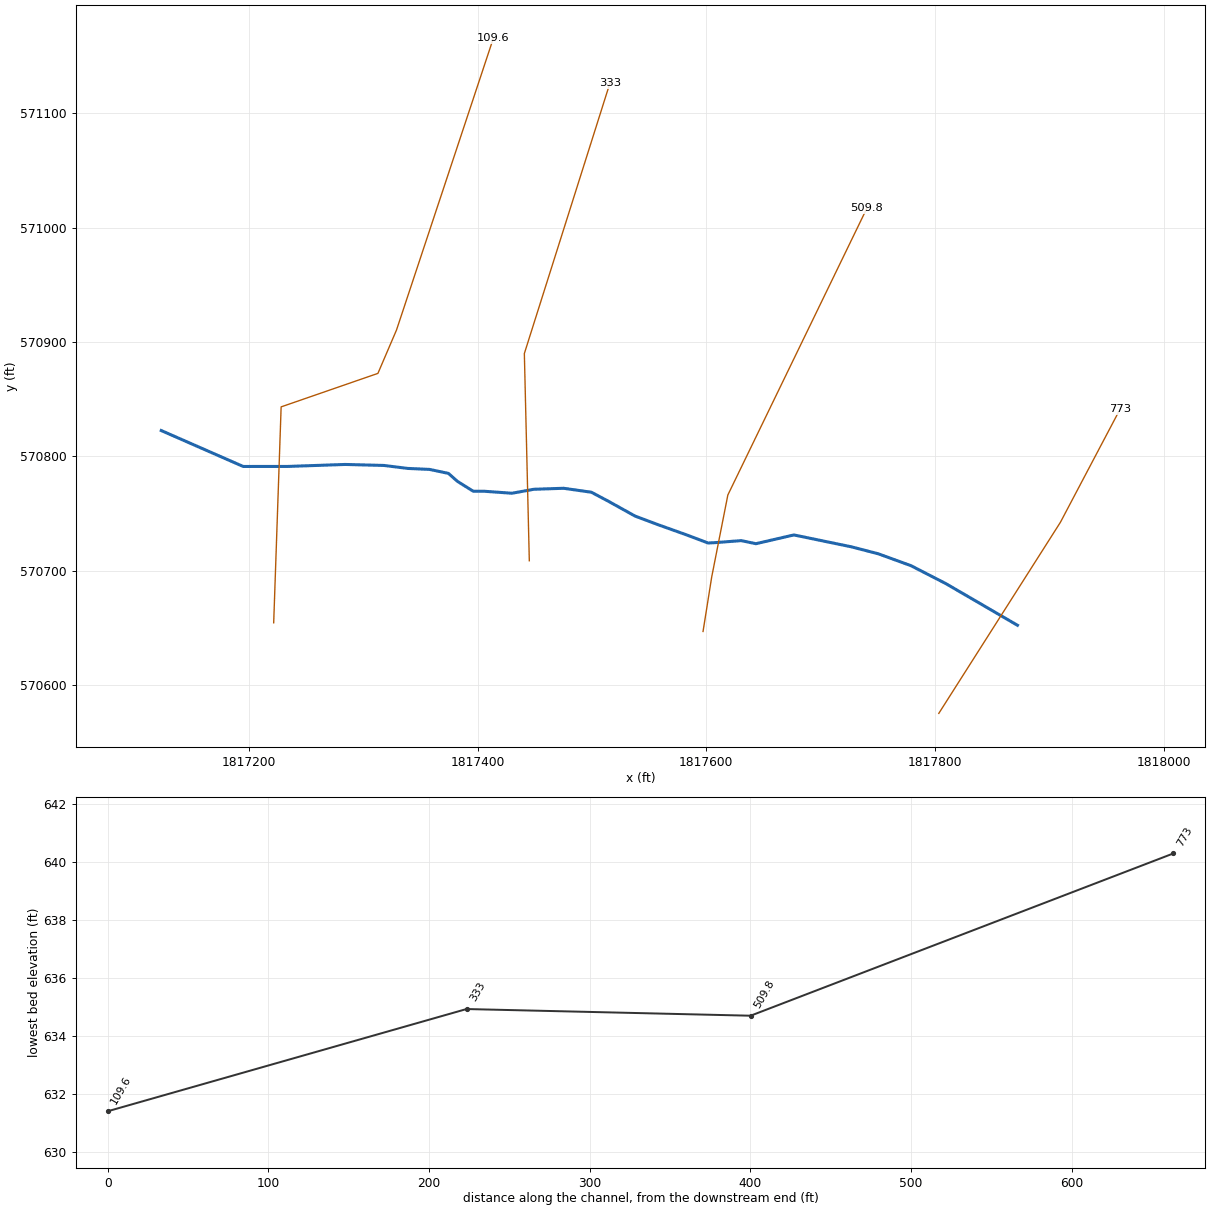
--- GOOSECR.prj (project) ---

Proj Title=GOOSECR
Current Plan=p01
Default Exp/Contr=0,0
English Units
Geom File=g01
Flow File=f01
Plan File=p01
BEGIN DESCRIPTION:
END DESCRIPTION:
DSS Export Rating Curves= 0
DSS Export Rating Curve Sorted= 0
DSS Export Volume Flow Curves= 0
DXF OffsetX= 0
DXF OffsetY= 0
DXF ScaleX= 0
DXF ScaleY= 0

--- GOOSECR.p01 (plan) ---

Plan Title=Floodplain
Program Version=4.00
Geom File=g01
Flow File=f01
K Sum by GR=0
Std Step Tol=0.01
Critical Tol=0.01
Num of Std Step Trials=20
Max Error Tol=0.3
Flow Tol Ratio=0.001
Split Flow NTrial=30
Split Flow Tol=0.02
Split Flow Ratio=0.02
Log Output Level=0
Friction Slope Method=1
Unsteady Friction Slope Method=2
Unsteady Bridges Friction Slope Method=1
Global Log Level=0
CheckData=False
Run HTab=0
Run UNet=0
Run PostProcess=0
UNET Theta=0
UNET Theta Warmup=0
UNET ZTol=0
UNET ZSATol=0
UNET MxIter=0
UNET MaxInSteps=0
UNET DtIC=0
UNET DtMin=0
UNET MaxCRTS=0
UNET WFStab=0
UNET SFStab=0
UNET WFX=0
UNET SFX=0
UNET DSS MLevel=0
UNET DZMax Abort=0
UNET Convert EG Bridges=0
UNET Use Existing IB Tables=0
UNET Froude Limit=0
UNET Froude Power=0
Write IC File=0
Echo Input=False
Echo Output=False
Write Detailed=0

--- GOOSECR.f01 (steady flow) ---

Flow Title=NFF Regression Equation
Program Version=4.10
Number of Profiles= 1
Profile Names=P100yr
River Rch & RM=GOOSECR,Main            ,773
 880.286
Boundary for River Rch & Prof#=GOOSECR,Main            , 1
Up Type= 0
Dn Type= 3
Dn Slope=0.016
DSS Import GetInterval= 0
DSS Import GetPeak= 0
DSS Import FillOption= 0

--- GOOSECR.g01 (geometry) ---

Geom Title=USGS 10m DEM
Program Version=4.10

River Reach=GOOSECR         ,Main
Reach XY= 29
     1817872.086      570652.323     1817809.412      570688.781
     1817779.031      570704.406     1817750.385      570714.823
     1817726.947      570720.899       1817676.6      570731.316
     1817643.382       570723.65     1817630.548      570726.345
     1817607.979      570724.609     1817601.548      570724.252
      1817582.85      570731.316     1817558.544      570739.996
     1817537.711      570747.809     1817514.274       570760.83
     1817499.517      570768.642     1817475.211      570772.114
     1817449.169      570771.246     1817430.072      570767.774
     1817405.767       570769.51     1817396.218       570769.51
     1817382.329      570778.191     1817374.517      570785.135
     1817358.024      570788.607     1817338.926      570789.475
     1817318.093       570792.08     1817284.239      570792.948
     1817233.892      570791.212     1817195.006      570791.192
     1817123.359      570822.603

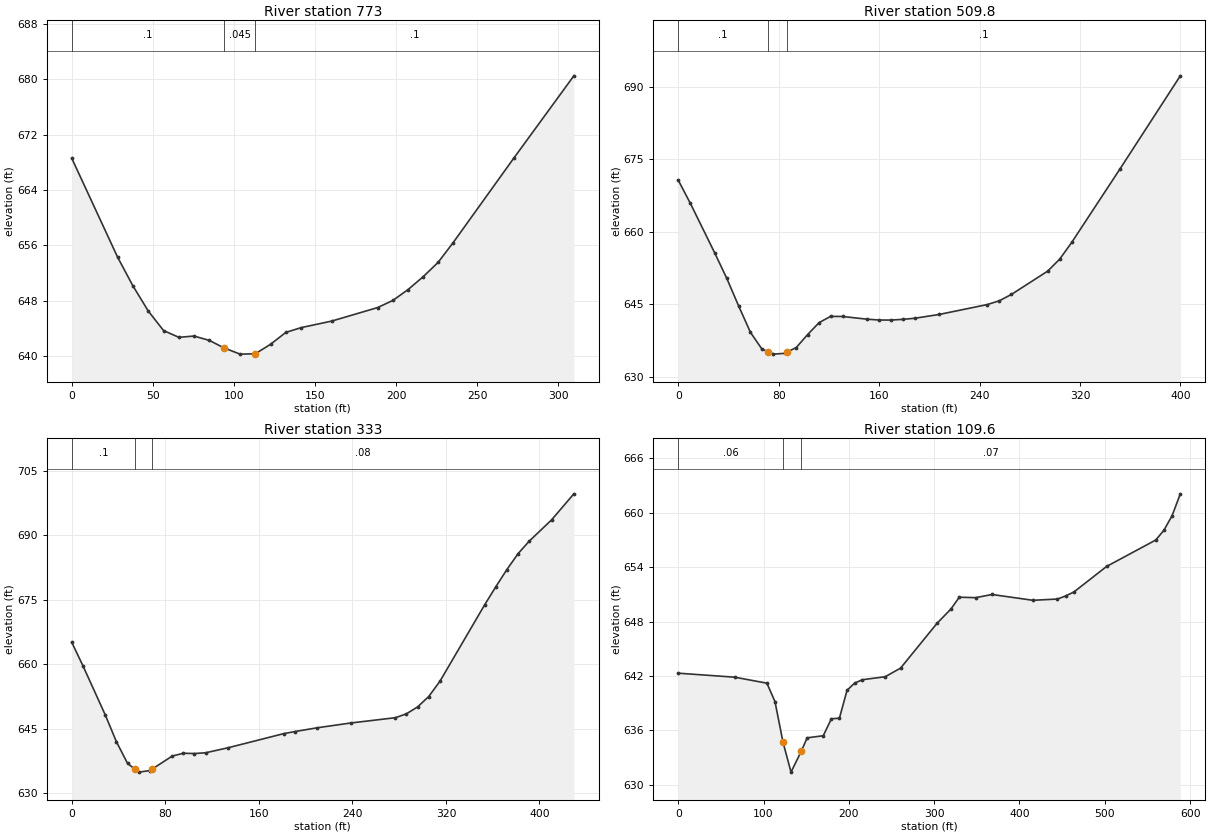
Type RM Length L Ch R = 1 ,773     ,254.8,263.2,271.4
XS GIS Cut Line= 3
     1817803.293      570575.283      1817909.63      570742.383
     1817961.713      570841.125
#Sta/Elev= 23
       0  668.58    28.3  654.28    37.7  650.16    47.2  646.51    56.6   643.7
      66  642.72    75.4   642.9    84.9  642.27    93.8   641.2   103.8  640.29
   113.2  640.34   122.6  641.71     132  643.42   141.5  644.12   160.3  645.06
   188.6  647.01   198.1  648.05   207.4  649.61   216.7  651.46     226  653.55
   235.3  656.41   272.5  668.55   309.7  680.49
#Mann= 3 , 0 , 0
       0      .1       0    93.8    .045       0   113.2      .1       0
Bank Sta=93.8,113.2
XS Rating Curve= 0 ,0
Exp/Cntr=0.3,0.1

Type RM Length L Ch R = 1 ,509.8   ,171.8,176.8,181.9
XS GIS Cut Line= 4
      1817597.13      570646.897     1817604.725       570694.64
     1817618.831      570766.255     1817740.359      571016.906
#Sta/Elev= 30
       0  670.71     9.7  665.88      29  655.68    38.7  650.36    48.3  644.56
    57.5  639.22    66.6  635.76    71.6  635.18    75.7   634.7    84.8  634.86
    86.6   635.1      94  636.07   103.1  638.76   112.2  641.22   121.3  642.51
   130.9  642.49   150.2  641.94   159.8  641.76   169.4  641.75     179   641.9
   188.6  642.13   207.8  642.91   246.2  644.96   255.8  645.75   265.4  647.06
   294.2  651.87   303.8  654.35   313.4  657.82   351.9  673.05   399.9   692.3
#Mann= 3 , 0 , 0
       0      .1       0    71.6    .045       0    86.6      .1       0
Bank Sta=71.6,86.6
XS Rating Curve= 0 ,0
Exp/Cntr=0.3,0.1

Type RM Length L Ch R = 1 ,333     ,224.4,223.3,221.5
XS GIS Cut Line= 3
      1817445.22      570708.746      1817440.88      570889.953
     1817515.749      571126.498
#Sta/Elev= 30
       0   665.1     9.5  659.69    28.6  648.26    38.2  641.99    47.7  636.97
      54  635.62    57.2  634.93    66.8  635.29      69  635.68    85.9  638.66
    95.4  639.32   104.9  639.25   114.5  639.43   133.6  640.59   181.3  643.88
   190.8  644.36   209.9  645.24   238.5  646.35   276.7  647.58   286.2  648.48
   295.8   650.1   305.3  652.51   314.9  656.07     353  673.77   362.6     678
   372.1  682.01   381.7  685.72   391.2  688.62   410.3  693.56   429.4  699.63
#Mann= 3 , 0 , 0
       0      .1       0      54    .045       0      69     .08       0
Bank Sta=54,69
XS Rating Curve= 0 ,0
Exp/Cntr=0.3,0.1

Type RM Length L Ch R = 1 ,109.6   ,118.3,109.6,101
XS GIS Cut Line= 5
     1817221.695      570654.493     1817228.206      570843.295
     1817312.841      570872.592     1817329.117      570910.569
     1817413.753      571165.561
#Sta/Elev= 30
       0  642.31    66.1  641.87   103.9  641.21   113.4  639.18   122.8  634.71
   132.2  631.41   144.3  633.73   151.1  635.19     170  635.42   179.5  637.29
   188.9  637.35   197.9  640.43   206.8  641.22   215.8  641.59   242.6  641.92
   260.6  642.87   303.3   647.8   319.8   649.4   329.4  650.68   348.6  650.63
   367.8  650.98   415.8  650.34   444.5  650.48   454.1  650.82   463.7  651.25
   502.1  654.07   559.7  656.98   569.3  658.06   578.9  659.67   588.5  662.07
#Mann= 3 , 0 , 0
       0     .06       0   122.8    .045       0   144.3     .07       0
Bank Sta=122.8,144.3
XS Rating Curve= 0 ,0
Exp/Cntr=0.3,0.1

Chan Stop Cuts=-1
Use User Specified Reach Order=0
Composite Channel Slope=5